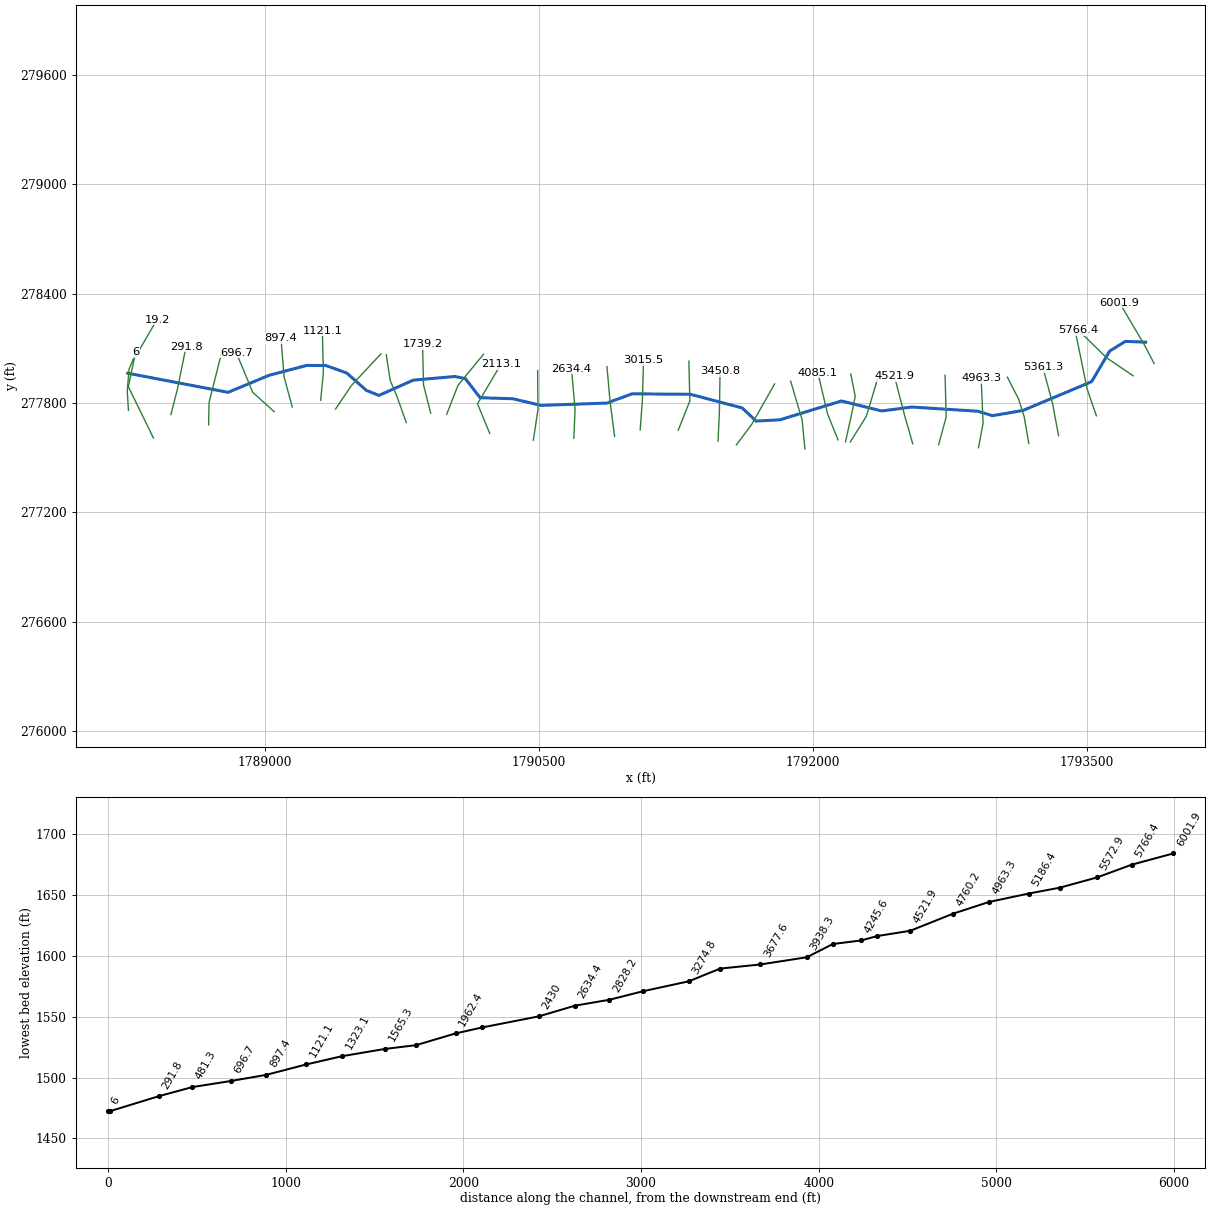
--- BrushyFk.prj (project) ---

Proj Title=BrushyFk
Current Plan=p01
Default Exp/Contr=0,0
English Units
Geom File=g01
Flow File=f01
Plan File=p01
BEGIN DESCRIPTION:
END DESCRIPTION:
DSS Export Rating Curves= 0
DSS Export Rating Curve Sorted= 0
DSS Export Volume Flow Curves= 0
DXF OffsetX= 0
DXF OffsetY= 0
DXF ScaleX= 0
DXF ScaleY= 0

--- BrushyFk.p01 (plan) ---

Plan Title=Floodplain
Program Version=4.00
Geom File=g01
Flow File=f01
K Sum by GR=0
Std Step Tol=0.01
Critical Tol=0.01
Num of Std Step Trials=20
Max Error Tol=0.3
Flow Tol Ratio=0.001
Split Flow NTrial=30
Split Flow Tol=0.02
Split Flow Ratio=0.02
Log Output Level=0
Friction Slope Method=1
Unsteady Friction Slope Method=2
Unsteady Bridges Friction Slope Method=1
Global Log Level=0
CheckData=False
Run HTab=0
Run UNet=0
Run PostProcess=0
UNET Theta=0
UNET Theta Warmup=0
UNET ZTol=0
UNET ZSATol=0
UNET MxIter=0
UNET MaxInSteps=0
UNET DtIC=0
UNET DtMin=0
UNET MaxCRTS=0
UNET WFStab=0
UNET SFStab=0
UNET WFX=0
UNET SFX=0
UNET DSS MLevel=0
UNET DZMax Abort=0
UNET Convert EG Bridges=0
UNET Use Existing IB Tables=0
UNET Froude Limit=0
UNET Froude Power=0
Write IC File=0
Echo Input=False
Echo Output=False
Write Detailed=0

--- BrushyFk.f01 (steady flow) ---

Flow Title=NFF Regression Equation
Program Version=4.00
Number of Profiles=1
Profile Names=P100yr
River Rch & RM=BrushyFk,Main      ,6001.9
581.7132
River Rch & RM=BrushyFk,Main      ,4245.6
613.8919
River Rch & RM=BrushyFk,Main      ,3938.3
675.4895
River Rch & RM=BrushyFk,Main      ,3015.5
691.6682
River Rch & RM=BrushyFk,Main      ,2113.1
757.1814
River Rch & RM=BrushyFk,Main      ,291.8
792.0120
Boundary for River Rch & Prof#=BrushyFk,Main      ,1
Up Type=0
Dn Type=3
Dn Slope=0.031444

--- BrushyFk.g01 (geometry) ---

Geom Title=USGS 10m DEM
Program Version=4.00

River Reach=BrushyFk        ,Main
Reach XY= 30
     1793822.206      278133.005     1793711.362      278137.708
     1793625.375      278084.637     1793526.623      277916.693
      1793150.54      277758.713     1792983.938      277730.051
     1792903.005      277754.404     1792542.356      277777.523
     1792376.651      277756.026     1792157.204      277810.664
     1791820.361      277707.413     1791690.542      277700.492
     1791613.874      277772.573     1791330.469      277847.388
     1791011.289      277849.914     1790873.529      277799.293
     1790513.179       277786.49     1790357.993       277823.03
     1790179.489      277828.578     1790098.876      277933.375
     1790041.551      277945.019     1789813.166      277924.907
     1789626.051      277841.255     1789557.368      277868.552
     1789449.502      277964.091     1789335.912      278005.036
     1789230.687      278005.916       1789024.2      277951.323
     1788800.105      277858.136     1788250.773      277963.029

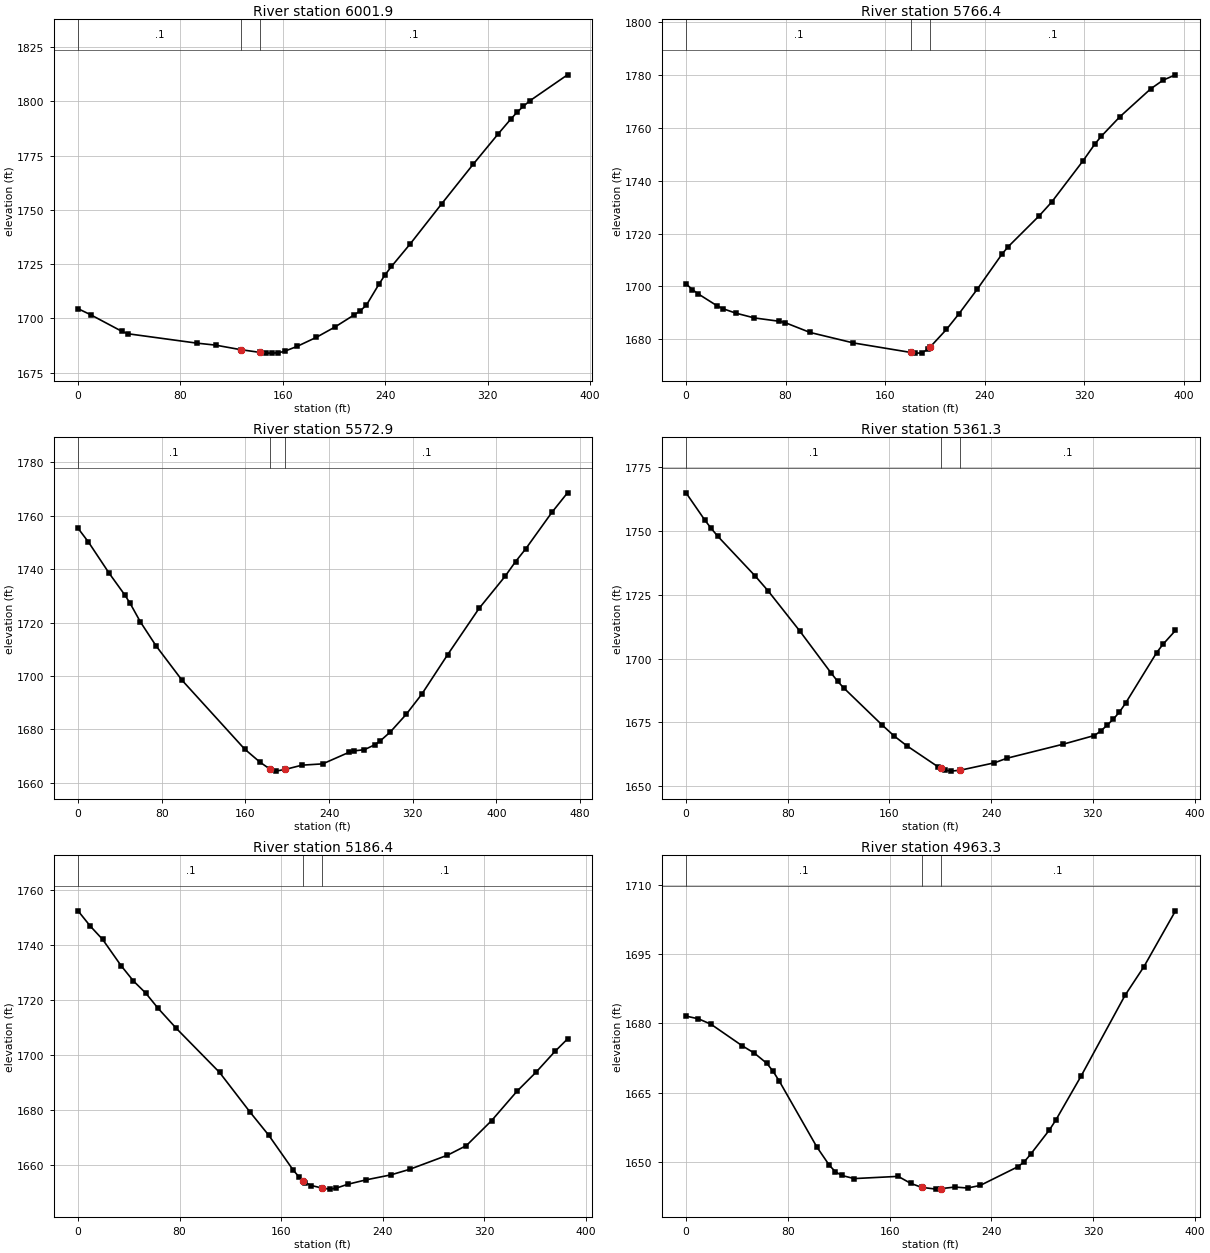
Type RM Length L Ch R = 1 ,6001.9  ,229.9,235.5,238.6
XS GIS Cut Line= 3
     1793868.358      278016.655     1793814.263      278120.547
     1793679.549      278348.962
#Sta/Elev= 30
       0 1704.51     9.8 1701.74    34.2 1694.09      39 1692.96    92.7 1688.65
   107.4 1687.73     127 1685.64     142 1684.39   146.6 1684.07   151.5 1684.04
   156.4 1684.19   161.3 1684.88   171.2 1687.17   185.9 1691.24   200.6 1696.04
   215.4 1701.55   220.3 1703.45   225.2 1706.12     235 1715.75   239.9 1720.19
   244.8 1723.94   259.5 1734.38   284.1 1752.87   308.6    1771   328.3 1785.12
   338.1 1791.89     343 1795.04   347.9 1797.77   352.8 1800.22   382.3 1812.22
#Mann= 3 , 0 , 0
       0      .1       0     127    .045       0     142      .1       0
Bank Sta=127,142
XS Rating Curve= 0 ,0
Exp/Cntr=0.3,0.1

Type RM Length L Ch R = 1 ,5766.4  ,208.8,193.5,180
XS GIS Cut Line= 3
     1793753.678      277948.892     1793609.354      278046.852
     1793452.815      278200.029
#Sta/Elev= 30
       0 1701.01       5 1698.82      10 1697.11    24.9 1692.67    29.9 1691.52
    39.9  1689.9    54.8 1688.08    74.8 1686.81    79.7 1686.28    99.7 1682.57
   134.6  1678.6   180.9 1674.99   184.4 1674.75   189.4  1674.8   194.3 1676.19
   195.9  1676.9   209.3 1683.71   219.2 1689.53   234.2 1699.02   254.1 1712.31
     259 1715.05   283.9 1726.72   293.9 1731.92   318.8 1747.33   328.7 1753.93
   333.7 1756.77   348.6 1764.14   373.5 1774.76   383.5 1778.05   393.4 1780.05
#Mann= 3 , 0 , 0
       0      .1       0   180.9    .045       0   195.9      .1       0
Bank Sta=180.9,195.9
XS Rating Curve= 0 ,0
Exp/Cntr=0.3,0.1

Type RM Length L Ch R = 1 ,5572.9  ,210.2,211.6,213
XS GIS Cut Line= 3
      1793552.72      277729.425     1793502.406      277875.196
     1793439.495      278182.559
#Sta/Elev= 30
       0 1755.33      10 1750.14    29.8 1738.46    44.8  1730.3    49.8  1727.2
    59.7 1720.19    74.6 1711.27    99.5 1698.36   159.2 1672.63   174.1 1667.65
   183.3 1665.15   189.1 1664.34   198.3    1665     214 1666.57   233.9 1667.06
   258.8 1671.35   263.8 1671.93   273.7 1672.36   283.7 1674.22   288.7 1675.59
   298.6 1679.04   313.6 1685.56   328.5  1693.1   353.4 1708.01   383.3 1725.27
   408.2  1737.3   418.2 1742.81   428.1 1747.69     453 1761.29   467.9  1768.6
#Mann= 3 , 0 , 0
       0      .1       0   183.3    .045       0   198.3      .1       0
Bank Sta=183.3,198.3
XS Rating Curve= 0 ,0
Exp/Cntr=0.3,0.1

Type RM Length L Ch R = 1 ,5361.3  ,174,174.9,175.8
XS GIS Cut Line= 3
     1793345.438      277620.881     1793311.877      277801.501
     1793259.338       277995.77
#Sta/Elev= 30
       0 1764.93    14.9 1754.17    19.9 1750.95    24.8    1748    54.6 1732.23
    64.6 1726.49    89.4 1710.83   114.2 1694.26   119.2 1691.11   124.1 1688.44
   153.9  1674.1   163.8 1669.59   173.8 1665.75   198.4  1657.5   200.5 1657.01
   203.4 1656.32   208.2 1655.86   215.5 1656.19   242.6 1659.12   252.4 1660.91
   296.6 1666.41   321.2 1669.82   326.1 1671.53     331 1673.76   335.9 1676.15
   340.8 1678.93   345.7 1682.46   370.2 1702.32   375.1 1705.53     385    1711
#Mann= 3 , 0 , 0
       0      .1       0   200.5    .045       0   215.5      .1       0
Bank Sta=200.5,215.5
XS Rating Curve= 0 ,0
Exp/Cntr=0.3,0.1

Type RM Length L Ch R = 1 ,5186.4  ,246,223.1,217.9
XS GIS Cut Line= 4
     1793182.699      277577.084     1793157.297       277725.11
      1793126.74      277821.273     1793065.541      277940.885
#Sta/Elev= 30
       0 1752.54     9.7 1746.94    19.4  1742.1    33.9 1732.55    43.6 1726.97
    53.3 1722.55      63 1717.01    77.5 1709.63   111.4 1693.63   135.6 1679.05
   150.2 1670.68   169.4 1658.01   174.2  1655.4   177.3 1654.11     179 1653.39
   183.8 1652.36   192.3 1651.42   198.2 1651.05     203 1651.37   212.6 1652.85
   227.1 1654.46   246.3 1656.24     261 1658.25   290.9 1663.42   305.8 1666.93
   325.7 1676.07   345.6 1686.73   360.6 1693.67   375.5 1701.26   385.4 1705.81
#Mann= 3 , 0 , 0
       0      .1       0   177.3    .045       0   192.3      .1       0
Bank Sta=177.3,192.3
XS Rating Curve= 0 ,0
Exp/Cntr=0.3,0.1

Type RM Length L Ch R = 1 ,4963.3  ,203.6,203,202.3
XS GIS Cut Line= 3
     1792907.121      277554.525     1792932.616      277689.161
     1792921.674      277936.496
#Sta/Elev= 30
       0 1681.58     9.8 1680.98    19.6 1679.82      44 1675.18    53.8 1673.54
    63.6 1671.33    68.5 1669.59    73.4 1667.46   102.8 1653.26   112.6 1649.31
   117.4 1647.89   122.4  1647.1   132.1 1646.42   166.7  1646.9   176.6 1645.38
   185.1 1644.53   196.4 1644.14   200.1 1644.24   211.3 1644.59   221.2 1644.38
   231.1 1644.93   260.8 1648.99   265.8 1650.07   270.7 1651.66   285.6 1656.97
   290.5 1659.05   310.3 1668.54     345 1686.09   359.8 1692.27   384.6 1704.35
#Mann= 3 , 0 , 0
       0      .1       0   185.1    .045       0   200.1      .1       0
Bank Sta=185.1,200.1
XS Rating Curve= 0 ,0
Exp/Cntr=0.3,0.1

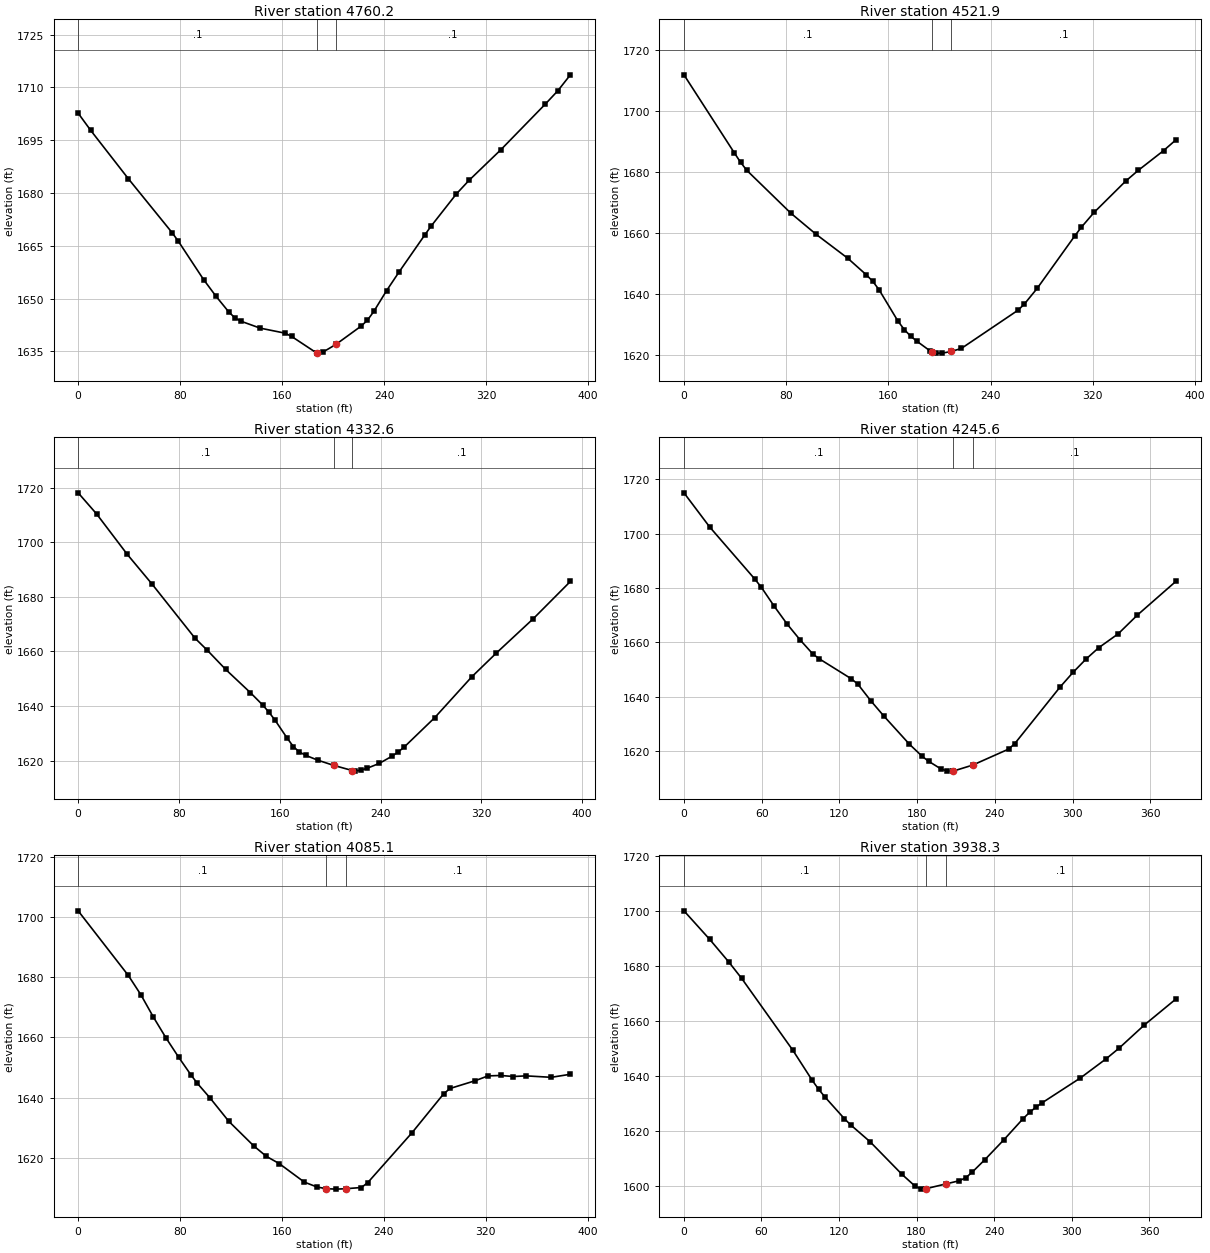
Type RM Length L Ch R = 1 ,4760.2  ,233.3,238.4,243.5
XS GIS Cut Line= 3
     1792689.038      277570.524     1792730.404      277722.413
     1792724.499      277951.129
#Sta/Elev= 30
       0 1702.66     9.8  1697.8    39.4 1684.03    73.8 1668.67    78.7 1666.22
    98.4 1655.39   108.2 1650.62   118.1 1646.22     123 1644.49   127.9 1643.53
   142.7 1641.59   162.4 1640.15   167.4 1639.24   187.2  1634.5   187.3 1634.48
   192.2 1634.81   202.2 1636.94   222.1 1642.18     227 1643.84     232 1646.34
     242 1652.24   251.9  1657.6   271.8 1667.97   276.8 1670.51   296.7 1679.69
   306.6 1683.54   331.5 1692.22   366.3 1705.15   376.3 1709.01   386.2 1713.56
#Mann= 3 , 0 , 0
       0      .1       0   187.2    .045       0   202.2      .1       0
Bank Sta=187.2,202.2
XS Rating Curve= 0 ,0
Exp/Cntr=0.3,0.1

Type RM Length L Ch R = 1 ,4521.9  ,201.6,189.2,176.9
XS GIS Cut Line= 3
     1792547.385      277576.301     1792503.926      277727.806
      1792446.66       277948.09
#Sta/Elev= 30
       0 1711.92    39.4 1686.31    44.3  1683.2    49.2 1680.55    83.7 1666.47
   103.4 1659.56   128.1 1651.72   142.8 1646.22   147.8 1644.09   152.7 1641.34
   167.5 1631.03   172.5 1628.24   177.4 1626.11   182.4 1624.41   192.2  1621.4
   194.3 1621.04   197.2 1620.54   202.2 1620.54   209.3  1621.1     217 1622.06
   261.5 1634.65   266.5 1636.71   276.4 1641.79     306 1659.12     311 1661.88
   320.9 1666.72   345.6 1676.99   355.5 1680.54   375.3 1687.02   385.2 1690.64
#Mann= 3 , 0 , 0
       0      .1       0   194.3    .045       0   209.3      .1       0
Bank Sta=194.3,209.3
XS Rating Curve= 0 ,0
Exp/Cntr=0.3,0.1

Type RM Length L Ch R = 1 ,4332.6  ,84.7,87,89.3
XS GIS Cut Line= 4
     1792205.824      277586.158     1792293.625      277726.907
     1792316.093      277801.501     1792357.963      277942.235
#Sta/Elev= 30
       0 1718.17    14.6 1710.45      39 1695.59    58.6 1684.73    92.7 1664.88
   102.5 1660.43   117.1  1653.4   136.6 1644.93   146.4 1640.39   151.2 1637.84
   156.1  1634.9   165.9 1628.19   170.8  1625.1   175.6 1623.13   180.5 1621.92
   190.2 1620.13   202.7 1618.24   217.7 1616.32   219.4 1616.12   224.3 1616.48
   229.2 1617.15   238.9 1618.94   248.7  1621.5   253.6 1623.02   258.5 1624.84
     283 1635.75   312.3 1650.67   331.9 1659.44   361.3 1672.07   390.6 1685.67
#Mann= 3 , 0 , 0
       0      .1       0   202.7    .045       0   217.7      .1       0
Bank Sta=202.7,217.7
XS Rating Curve= 0 ,0
Exp/Cntr=0.3,0.1

Type RM Length L Ch R = 1 ,4245.6  ,150.8,160.5,170.1
XS GIS Cut Line= 4
     1792179.487      277586.706     1792219.031      277766.451
     1792232.512      277836.551     1792208.246      277958.777
#Sta/Elev= 30
       0 1715.04    19.9 1702.44    54.7 1683.29    59.7  1680.3    69.6 1673.34
    79.6 1666.76    89.5 1660.99    99.5  1655.7   104.5 1653.93   129.3 1646.55
   134.3 1644.58   144.2 1638.51   154.2 1632.93   174.1 1622.48     184    1618
   188.8 1616.24   198.3 1613.43   203.1 1612.63   207.8 1612.59   207.9  1612.6
   222.9 1614.81   250.7 1620.71   255.4 1622.73   290.3 1643.51   300.3  1648.9
   310.3  1653.8   320.2 1658.02   335.2 1663.12   350.1 1670.06     380 1682.54
#Mann= 3 , 0 , 0
       0      .1       0   207.9    .045       0   222.9      .1       0
Bank Sta=207.9,222.9
XS Rating Curve= 0 ,0
Exp/Cntr=0.3,0.1

Type RM Length L Ch R = 1 ,4085.1  ,145.7,146.8,147.9
XS GIS Cut Line= 3
     1792138.483      277597.727     1792081.526      277739.489
     1792027.603      277966.866
#Sta/Elev= 30
       0 1702.07    39.4  1680.6    49.3 1674.16    59.1 1666.76      69 1659.84
    78.8 1653.52    88.7 1647.49    93.6 1644.77   103.5 1639.94   118.3 1632.15
     138 1623.94   147.8 1620.51   157.8 1618.14   177.6 1611.96   187.6 1610.33
     195 1609.77   202.5 1609.63     210 1609.76   222.4 1610.17   227.4 1611.79
   262.2 1628.38     287 1641.29     292 1643.06   311.9 1645.66   321.8 1647.24
   331.8 1647.38   341.7 1647.04   351.7 1647.25   371.5 1646.77   386.5 1647.78
#Mann= 3 , 0 , 0
       0      .1       0     195    .045       0     210      .1       0
Bank Sta=195,210
XS Rating Curve= 0 ,0
Exp/Cntr=0.3,0.1

Type RM Length L Ch R = 1 ,3938.3  ,278.9,260.8,242.7
XS GIS Cut Line= 3
     1791957.079      277548.053     1791942.224      277706.236
     1791879.314      277919.233
#Sta/Elev= 30
       0 1700.12    19.9 1689.74    34.8 1681.43    44.7 1675.49    84.4 1649.25
    99.3 1638.37   104.3 1635.07   109.2 1632.27   124.1 1624.45   129.1 1622.12
     144 1616.04   168.8 1604.11   178.6 1599.96   183.6 1598.75   187.6 1598.95
   202.6 1600.62   213.2 1601.82   218.1 1602.89     223 1604.88   232.9 1609.47
   247.7 1616.76   262.5 1624.41   267.5  1626.7   272.4 1628.59   277.3 1630.21
   306.9 1639.25   326.7 1646.19   336.6 1650.01   356.3 1658.51     381 1668.08
#Mann= 3 , 0 , 0
       0      .1       0   187.6    .045       0   202.6      .1       0
Bank Sta=187.6,202.6
XS Rating Curve= 0 ,0
Exp/Cntr=0.3,0.1

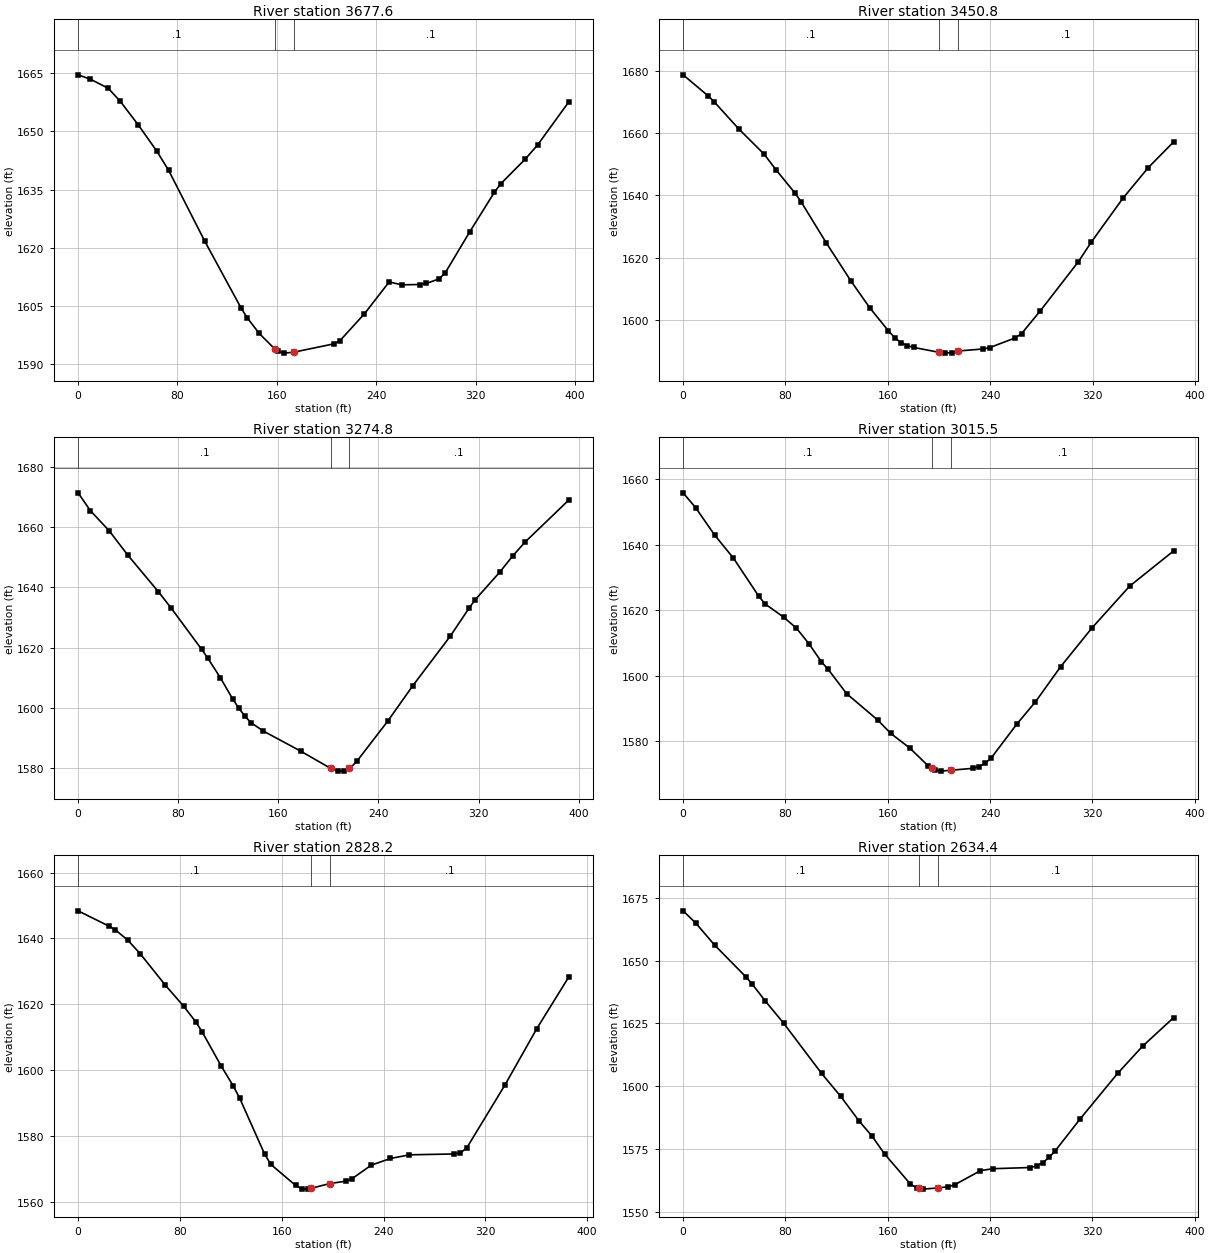
Type RM Length L Ch R = 1 ,3677.6  ,213.8,226.7,239.7
XS GIS Cut Line= 3
     1791582.296      277569.798     1791666.317       277682.87
     1791791.239      277903.955
#Sta/Elev= 30
       0 1664.59     9.7  1663.5    24.3 1661.12      34 1657.75    48.6 1651.62
    63.2 1644.99    72.9 1639.97     102 1621.68   131.2 1604.48     136 1602.02
   145.8 1597.93   158.4 1593.89   160.8 1593.29   165.8 1592.85   173.4 1593.08
   205.6 1595.22   210.6    1596   230.5 1602.99   250.4 1611.21   260.4 1610.46
   275.3 1610.54   280.3  1610.8   290.2 1611.96   295.2 1613.38   315.1 1624.04
   335.1 1634.32     340 1636.44     360 1642.89   369.9 1646.53   394.8 1657.54
#Mann= 3 , 0 , 0
       0      .1       0   158.4    .045       0   173.4      .1       0
Bank Sta=158.4,173.4
XS Rating Curve= 0 ,0
Exp/Cntr=0.3,0.1

Type RM Length L Ch R = 1 ,3450.8  ,176.3,176,175.6
XS GIS Cut Line= 3
     1791481.725      277590.129     1791489.268      277750.274
     1791492.863      277973.157
#Sta/Elev= 30
       0 1678.67    19.4 1671.99    24.3 1670.02    43.7 1661.24    63.2 1653.29
    72.9 1648.07    87.4 1640.78    92.3 1637.89   111.7 1624.91   131.2 1612.54
   145.8 1604.01   160.3 1596.65   165.3 1594.43   170.2 1592.78   175.2 1591.86
   180.1 1591.28     200 1589.71   204.9 1589.45   209.9 1589.64     215 1590.13
   234.6  1590.8   239.6 1591.23   259.4 1594.32   264.4 1595.68   279.2 1603.07
   308.9 1618.81   318.8 1624.98   343.6  1639.1   363.4 1648.91   383.2 1657.17
#Mann= 3 , 0 , 0
       0      .1       0     200    .045       0     215      .1       0
Bank Sta=200,215
XS Rating Curve= 0 ,0
Exp/Cntr=0.3,0.1

Type RM Length L Ch R = 1 ,3274.8  ,260.5,259.3,258.1
XS GIS Cut Line= 3
     1791263.685      277649.893     1791327.498      277810.488
     1791322.201      278029.553
#Sta/Elev= 30
       0 1671.38     9.9 1665.42    24.7 1658.87    39.5 1650.83    64.2 1638.54
    74.1  1633.3    98.8  1619.4   103.7 1616.48   113.6 1610.08   123.4 1603.06
   128.4 1599.97   133.3 1597.23   138.2  1595.1   148.1 1592.31   177.8 1585.68
   201.8 1579.95   207.7 1579.03   212.6 1579.05   216.8 1579.95   217.6 1580.13
   222.6 1582.23   247.5 1595.66   267.4 1607.36   297.3 1623.77   312.2    1633
   317.2 1635.86   337.2  1645.2   347.1 1650.36   357.1 1655.03   391.9 1668.92
#Mann= 3 , 0 , 0
       0      .1       0   201.8    .045       0   216.8      .1       0
Bank Sta=201.8,216.8
XS Rating Curve= 0 ,0
Exp/Cntr=0.3,0.1

Type RM Length L Ch R = 1 ,3015.5  ,183.8,187.3,189.9
XS GIS Cut Line= 3
     1791055.595      277651.277     1791067.768      277813.184
     1791074.059       278034.27
#Sta/Elev= 30
       0  1655.8     9.8 1651.29    24.6 1642.94    39.4 1635.84      59 1624.32
      64 1621.91    78.7  1617.8    88.6 1614.48    98.4 1609.72   108.2 1604.17
   113.2    1602   127.9 1594.46   152.5  1586.3   162.4 1582.31   177.1  1577.9
   191.8 1572.36   194.4 1571.76   196.8  1571.2   201.7 1570.81   209.4 1571.08
   226.3 1571.66   231.2  1572.2   236.1 1573.16     241 1574.87   260.7 1585.06
   275.4 1591.92   295.1 1602.66   319.6  1614.5   349.1 1627.29   383.5 1638.06
#Mann= 3 , 0 , 0
       0      .1       0   194.4    .045       0   209.4      .1       0
Bank Sta=194.4,209.4
XS Rating Curve= 0 ,0
Exp/Cntr=0.3,0.1

Type RM Length L Ch R = 1 ,2828.2  ,196.6,193.8,191.9
XS GIS Cut Line= 3
     1790915.768      277616.103     1790891.138      277804.929
      1790873.74      277999.072
#Sta/Elev= 30
       0  1648.4    24.4 1643.73    29.3 1642.61    39.1 1639.48    48.8 1635.38
    68.4  1625.9      83 1619.41    92.8  1614.5    97.6 1611.56   112.3 1601.36
   122.1  1595.1     127 1591.48   146.5 1574.58   151.4  1571.4   170.9    1565
   175.8 1563.93   180.7 1563.87   182.9  1564.1   197.9 1565.57   210.4 1566.29
   215.4 1567.08   230.4 1571.15   245.4 1573.18   260.4 1574.29   295.4 1574.55
   300.4 1574.87   305.4  1576.4   335.4  1595.5   360.4  1612.6   385.4 1628.21
#Mann= 3 , 0 , 0
       0      .1       0   182.9    .045       0   197.9      .1       0
Bank Sta=182.9,197.9
XS Rating Curve= 0 ,0
Exp/Cntr=0.3,0.1

Type RM Length L Ch R = 1 ,2634.4  ,204.1,204.4,204.7
XS GIS Cut Line= 3
       1790692.4      277606.384     1790699.291      277763.755
     1790679.581      277988.369
#Sta/Elev= 30
       0 1669.77     9.8 1664.96    24.6 1656.17    49.2 1643.44    54.2 1640.52
      64 1634.06    78.8 1624.94   108.3 1605.06   123.1 1596.02   137.8    1586
   147.7 1580.14   157.5 1573.04   177.5 1561.17   182.5  1559.5   184.1 1559.35
   187.5 1559.02   199.1 1559.48   207.5 1560.01   212.5 1560.78   232.5 1566.38
   242.4 1567.15   271.6 1567.62   276.4 1568.25   281.3 1569.61   286.2 1571.65
     291 1574.29   310.5 1586.99   339.7 1605.05   359.2 1615.87   383.5 1627.26
#Mann= 3 , 0 , 0
       0      .1       0   184.1    .045       0   199.1      .1       0
Bank Sta=184.1,199.1
XS Rating Curve= 0 ,0
Exp/Cntr=0.3,0.1

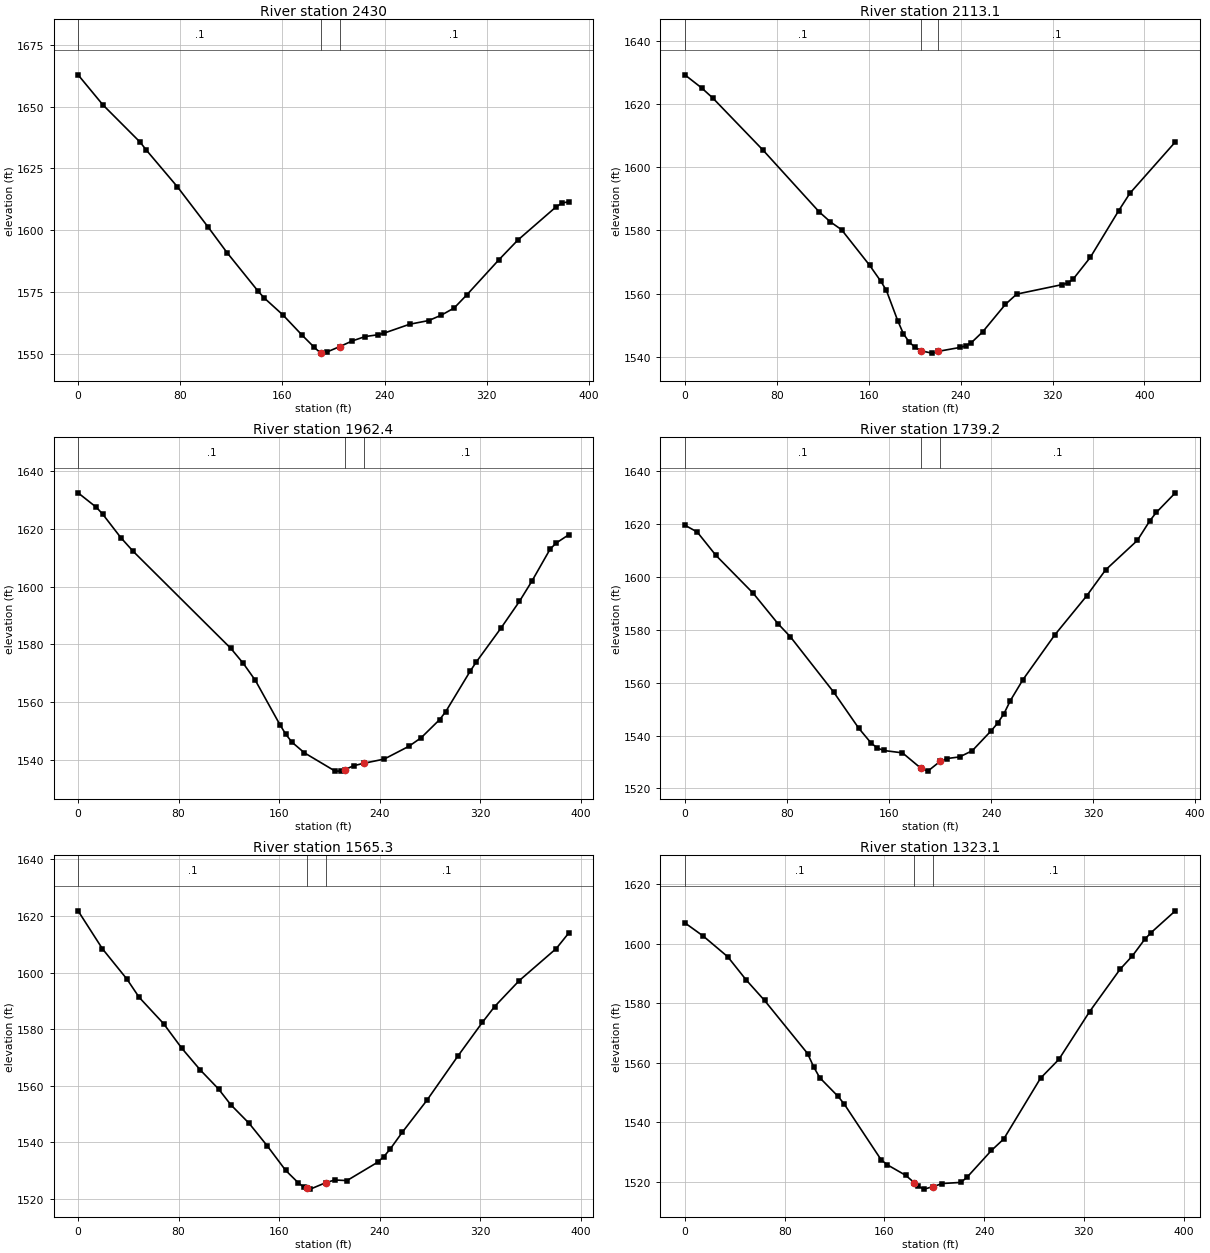
Type RM Length L Ch R = 1 ,2430    ,329.3,316.9,304.5
XS GIS Cut Line= 3
     1790470.886      277595.572      1790496.18      277763.755
     1790494.449      277977.695
#Sta/Elev= 30
       0 1662.82    19.4 1650.69    48.6 1635.57    53.4 1632.39    77.8 1617.49
     102  1601.1   116.6  1590.9   140.9 1575.31   145.8  1572.5   160.4 1565.66
     175 1557.69     185 1552.52   189.9 1550.25     190 1550.21     195  1550.7
   204.9 1552.86   214.8 1555.17   224.8 1556.92   234.8 1557.64   239.7 1558.32
   259.6  1561.9   274.6  1563.4   284.5  1565.6   294.5 1568.49   304.4 1573.81
   329.3 1587.88   344.2  1595.9   374.1 1609.33     379 1610.96     384 1611.45
#Mann= 3 , 0 , 0
       0      .1       0   189.9    .045       0   204.9      .1       0
Bank Sta=189.9,204.9
XS Rating Curve= 0 ,0
Exp/Cntr=0.3,0.1

Type RM Length L Ch R = 1 ,2113.1  ,154.5,150.7,146.8
XS GIS Cut Line= 3
     1790232.109      277632.956     1790165.451       277795.21
     1790293.355      278011.723
#Sta/Elev= 30
       0 1629.18    14.6 1625.04    24.4 1621.81    68.2  1605.3   116.9 1585.84
   126.7 1582.66   136.4 1580.19   160.8 1568.95   170.5 1563.92   175.4    1561
   185.3  1551.4   190.2  1547.3   195.1 1544.74   200.1 1543.04   205.2 1541.93
   214.9 1541.16   220.2  1541.7   239.5 1542.96   244.4 1543.45   249.4 1544.48
   259.2 1547.88     279 1556.58   288.8 1559.82   328.3 1562.82   333.2 1563.31
   338.1 1564.63   352.9 1571.44   377.6 1586.21   387.4 1591.74   426.9 1607.95
#Mann= 3 , 0 , 0
       0      .1       0   205.2    .045       0   220.2      .1       0
Bank Sta=205.2,220.2
XS Rating Curve= 0 ,0
Exp/Cntr=0.3,0.1

Type RM Length L Ch R = 1 ,1962.4  ,206.2,223.2,240.2
XS GIS Cut Line= 3
     1789996.838      277738.019     1790058.503      277896.765
     1790198.231      278066.746
#Sta/Elev= 30
       0 1632.39    14.6 1627.37    19.5 1625.08    34.1 1616.86    43.8  1612.2
   121.6 1578.62   131.4  1573.5   141.1 1567.57   160.6 1552.29   165.4  1548.9
   170.3 1546.19   180.1 1542.55   204.5 1536.24   209.4 1536.22   212.5 1536.75
   219.2 1538.08   227.5 1538.94   243.6 1540.38   263.2 1544.79     273 1547.74
   287.7 1554.01   292.6 1556.79   312.1  1570.8     317 1573.99   336.6 1585.68
   351.2 1594.86     361 1601.76   375.7 1612.97   380.6 1615.08   390.3 1617.85
#Mann= 3 , 0 , 0
       0      .1       0   212.5    .045       0   227.5      .1       0
Bank Sta=212.5,227.5
XS Rating Curve= 0 ,0
Exp/Cntr=0.3,0.1

Type RM Length L Ch R = 1 ,1739.2  ,165.4,173.9,182.5
XS GIS Cut Line= 3
     1789909.035      277743.661     1789869.771      277899.462
     1789864.576      278123.267
#Sta/Elev= 30
       0 1619.64     9.7 1617.04    24.3 1608.24    53.6 1593.86      73 1582.36
    82.8 1577.35   116.8 1556.37   136.3 1542.81   146.1 1537.13   150.9 1535.32
   155.8 1534.38   170.6 1533.47   185.1 1527.63   190.5 1526.56   200.1 1530.26
   205.4 1531.32   215.4 1531.94   225.3 1534.28   240.3 1541.92   245.2  1544.7
   250.2 1548.34   255.2 1553.27   265.1 1561.22     290 1578.11   314.9 1592.82
   329.8 1602.69   354.7 1613.86   364.6 1621.37   369.6 1624.45   384.5 1631.88
#Mann= 3 , 0 , 0
       0      .1       0   185.1    .045       0   200.1      .1       0
Bank Sta=185.1,200.1
XS Rating Curve= 0 ,0
Exp/Cntr=0.3,0.1

Type RM Length L Ch R = 1 ,1565.3  ,268.6,242.2,215.8
XS GIS Cut Line= 4
     1789775.745       277691.93     1789721.482      277842.842
      1789687.33      277923.727     1789666.089      278064.277
#Sta/Elev= 30
       0 1621.81    19.4 1608.39    38.9 1597.68    48.6 1591.26      68 1581.98
    82.6 1573.24    97.2 1565.62   111.8 1558.87   121.5 1553.33   136.1 1546.75
   150.6 1538.76   165.2 1530.12     175 1525.84   179.9 1524.09   182.2 1523.81
   184.8  1523.5   197.2  1525.8   204.3 1526.73     214 1526.52   238.4    1533
   243.3 1534.99   248.2 1537.54     258 1543.58   277.6 1554.88   302.1 1570.41
   321.7 1582.38   331.5    1588   351.1 1597.17   380.5 1608.47   390.3 1613.87
#Mann= 3 , 0 , 0
       0      .1       0   182.2    .045       0   197.2      .1       0
Bank Sta=182.2,197.2
XS Rating Curve= 0 ,0
Exp/Cntr=0.3,0.1

Type RM Length L Ch R = 1 ,1323.1  ,184.5,202,219.5
XS GIS Cut Line= 3
     1789388.152      277766.289     1789476.131      277896.765
     1789637.002       278069.32
#Sta/Elev= 30
       0 1607.03    14.8 1602.56    34.4 1595.62    49.2 1587.82    63.9 1580.94
    98.4  1563.1   103.3  1558.6   108.2 1554.95   122.9 1548.67   127.9 1546.04
   157.4 1527.37   162.3  1525.7     177 1522.17     184 1519.67   186.9 1518.49
   191.8 1517.51     199 1518.34   206.5  1519.4   221.3 1519.77   226.2 1521.47
   245.8  1530.5   255.7 1534.36   285.2  1554.8   299.9 1561.12   324.5 1577.15
     349 1591.43   358.9 1595.94   368.7 1601.46   373.6 1603.64   393.3 1611.07
#Mann= 3 , 0 , 0
       0      .1       0     184    .045       0     199      .1       0
Bank Sta=184,199
XS Rating Curve= 0 ,0
Exp/Cntr=0.3,0.1

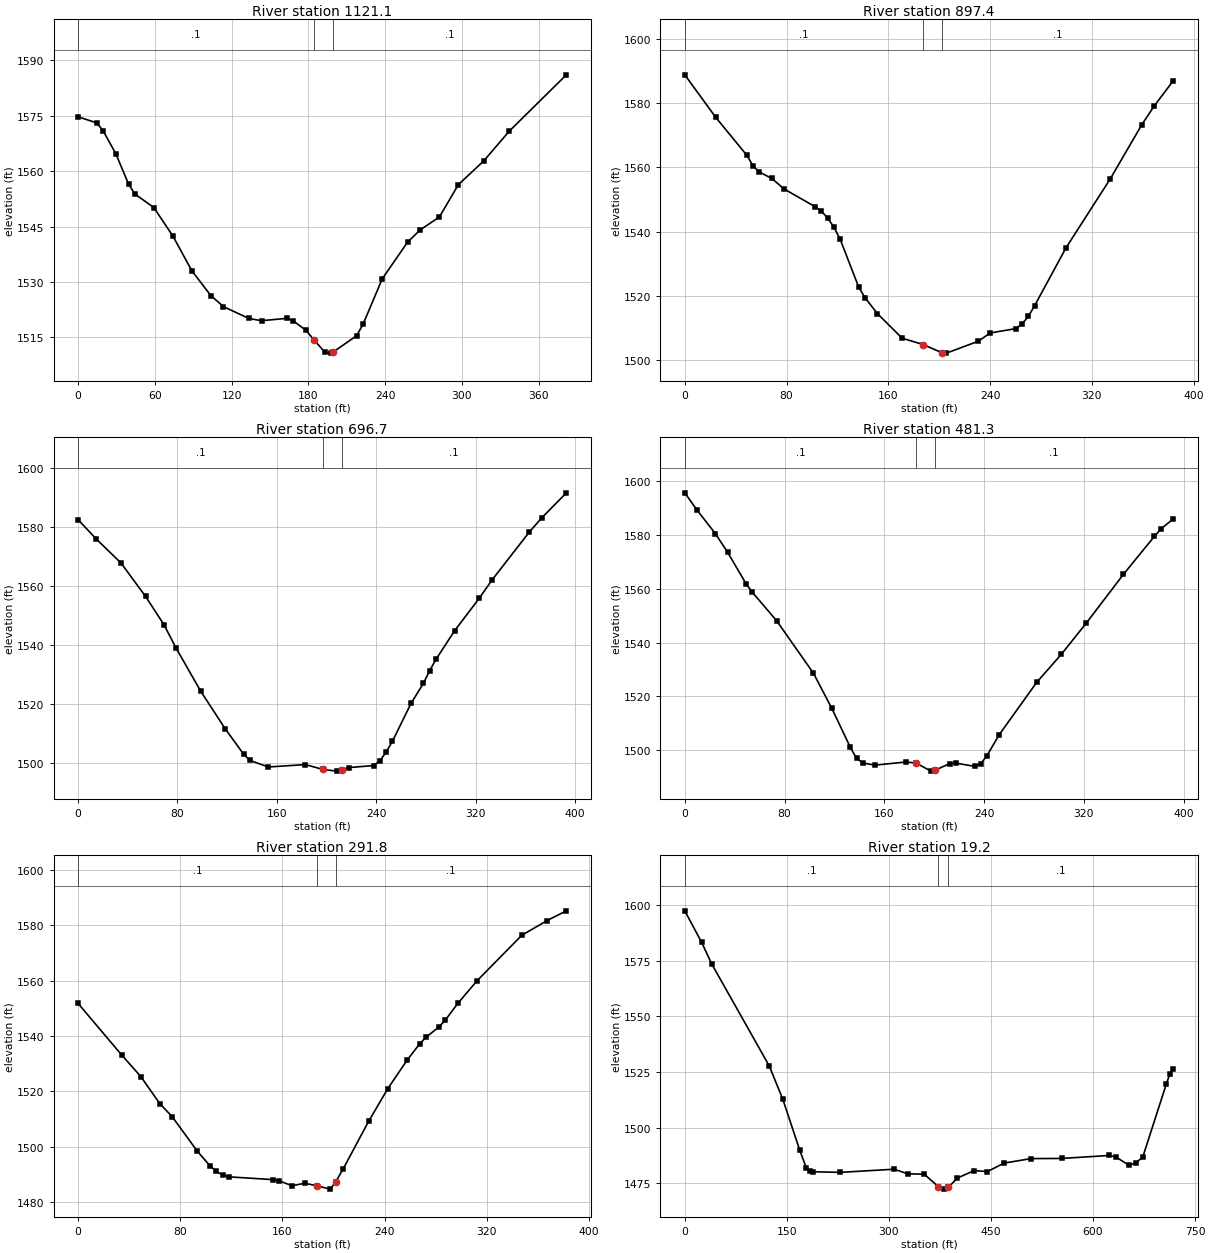
Type RM Length L Ch R = 1 ,1121.1  ,222.6,223.7,224.8
XS GIS Cut Line= 3
     1789306.945       277814.27      1789321.55      277966.866
     1789316.158      278195.141
#Sta/Elev= 30
       0 1574.72    14.8 1573.05    19.8 1570.84    29.7 1564.63    39.6 1556.44
    44.5  1553.8    59.3 1550.14    74.2  1542.4      89 1533.01   103.8 1526.31
   113.7 1523.31   133.5 1520.11   143.4  1519.5   163.2 1520.14   168.2 1519.47
   178.1  1516.9   184.2 1514.41     193  1510.9     198 1510.72   199.2 1510.96
   217.8 1515.46   222.8 1518.58   237.7 1530.81   257.5 1540.77   267.5 1544.12
   282.4 1547.59   297.2 1556.34   317.1 1562.79     337 1570.84   381.6 1586.08
#Mann= 3 , 0 , 0
       0      .1       0   184.2    .045       0   199.2      .1       0
Bank Sta=184.2,199.2
XS Rating Curve= 0 ,0
Exp/Cntr=0.3,0.1

Type RM Length L Ch R = 1 ,897.4   ,193.6,200.8,208
XS GIS Cut Line= 3
     1789151.313      277777.584     1789106.756        277942.6
     1789089.633      278154.894
#Sta/Elev= 30
       0 1588.72    24.4 1575.46    48.8  1563.7    53.7  1560.4    58.6 1558.49
    68.4 1556.52    78.1 1553.23   102.6 1547.69   107.4 1546.33   112.3 1544.18
   117.2 1541.39   122.1 1537.63   136.7 1522.75   141.6 1519.47   151.4  1514.5
   170.9 1506.84   187.5 1504.87   202.5 1502.26   205.6 1502.21   230.4 1505.86
   240.3  1508.5   260.1 1509.82     265 1511.19     270 1513.63   274.9 1516.89
   299.7 1534.98   334.4 1556.35   359.1 1573.12     369 1579.05   383.9 1586.86
#Mann= 3 , 0 , 0
       0      .1       0   187.5    .045       0   202.5      .1       0
Bank Sta=187.5,202.5
XS Rating Curve= 0 ,0
Exp/Cntr=0.3,0.1

Type RM Length L Ch R = 1 ,696.7   ,229.8,215.3,200.9
XS GIS Cut Line= 3
     1789052.332      277751.996       1788935.1       277858.12
     1788845.238       278075.26
#Sta/Elev= 30
       0 1582.59    14.8 1575.95    34.6 1567.86    54.4 1556.48    69.2 1546.89
    79.1 1538.84    98.8 1524.27   118.6 1511.46   133.4 1502.84   138.4 1500.76
   153.2 1498.54   183.1 1499.35   197.3 1497.69   208.1 1497.13   212.3 1497.61
   218.1 1498.34   238.1 1499.03   243.1 1500.69   248.1 1503.63   253.1 1507.27
   268.1 1520.16   278.1 1526.99   283.1  1531.3   288.1 1535.06   303.1  1544.8
   323.1 1555.91   333.1 1561.98   363.1 1578.26   373.1  1583.1   393.1 1591.67
#Mann= 3 , 0 , 0
       0      .1       0   197.3    .045       0   212.3      .1       0
Bank Sta=197.3,212.3
XS Rating Curve= 0 ,0
Exp/Cntr=0.3,0.1

Type RM Length L Ch R = 1 ,481.3   ,188.5,189.5,190.5
XS GIS Cut Line= 3
     1788693.469      277679.636      1788696.04        277802.4
     1788761.647      278063.029
#Sta/Elev= 30
       0 1595.67     9.8 1589.27    24.6 1580.46    34.4 1573.51    49.1 1561.88
      54 1558.79    73.7 1548.07   103.1 1528.63   117.9 1515.51   132.7 1501.05
   137.7 1496.96   142.7 1495.19   152.6 1494.42   177.5 1495.56   185.4 1495.18
   197.4 1492.17   200.4 1492.46   212.4 1494.97   217.4 1495.14   232.3 1493.96
   237.3 1494.92   242.2 1497.87   252.2 1505.77   282.1 1525.15     302 1535.67
   321.9 1547.21   351.7 1565.36   376.6  1579.5   381.6 1582.16   391.6 1585.97
#Mann= 3 , 0 , 0
       0      .1       0   185.4    .045       0   200.4      .1       0
Bank Sta=185.4,200.4
XS Rating Curve= 0 ,0
Exp/Cntr=0.3,0.1

Type RM Length L Ch R = 1 ,291.8   ,272.8,272.6,272.4
XS GIS Cut Line= 3
     1788487.165      277735.743     1788523.485      277878.791
     1788570.028      278108.869
#Sta/Elev= 30
       0 1551.83    34.4 1533.04    49.2 1525.34      64 1515.58    73.8  1510.8
    93.5 1498.31   103.3  1493.1   108.2 1491.06   113.2 1489.73   118.1 1489.08
   152.6 1488.08   157.6 1487.59   167.6 1485.88   177.6 1486.77   186.8 1485.87
   197.5 1484.64   201.8 1487.29   207.5 1491.89   227.5 1509.14   242.5 1520.96
   257.5 1531.19   267.4 1537.12   272.4 1539.54   282.4 1543.21   287.4 1545.66
   297.4 1551.84   312.4 1559.98   347.4 1576.42   367.3 1581.76   382.3 1585.26
#Mann= 3 , 0 , 0
       0      .1       0   186.8    .045       0   201.8      .1       0
Bank Sta=186.8,201.8
XS Rating Curve= 0 ,0
Exp/Cntr=0.3,0.1

Type RM Length L Ch R = 1 ,19.2    ,10.2,13.3,16.2
XS GIS Cut Line= 4
     1788391.601      277607.667     1788254.229      277888.821
     1788286.283      278041.762     1788410.833      278256.978
#Sta/Elev= 30
       0 1597.31    24.8 1583.15    39.7 1573.42   124.2 1527.69     144 1512.83
   168.9    1490   178.8 1481.78   183.8 1480.45   188.8 1480.25   228.5 1479.99
     308 1481.39   327.6 1479.32     352 1479.15   372.5 1473.62   381.3 1472.46
   387.5 1473.32   400.8 1477.45   425.2 1480.76   444.8 1480.35   469.2 1484.13
     509 1486.16   553.7 1486.22   623.4 1487.55   633.3 1486.93   653.2  1483.1
   663.1 1484.31   673.1 1486.84   707.9 1519.81   712.9 1524.13   717.8 1526.27
#Mann= 3 , 0 , 0
       0      .1       0   372.5    .045       0   387.5      .1       0
Bank Sta=372.5,387.5
XS Rating Curve= 0 ,0
Exp/Cntr=0.3,0.1

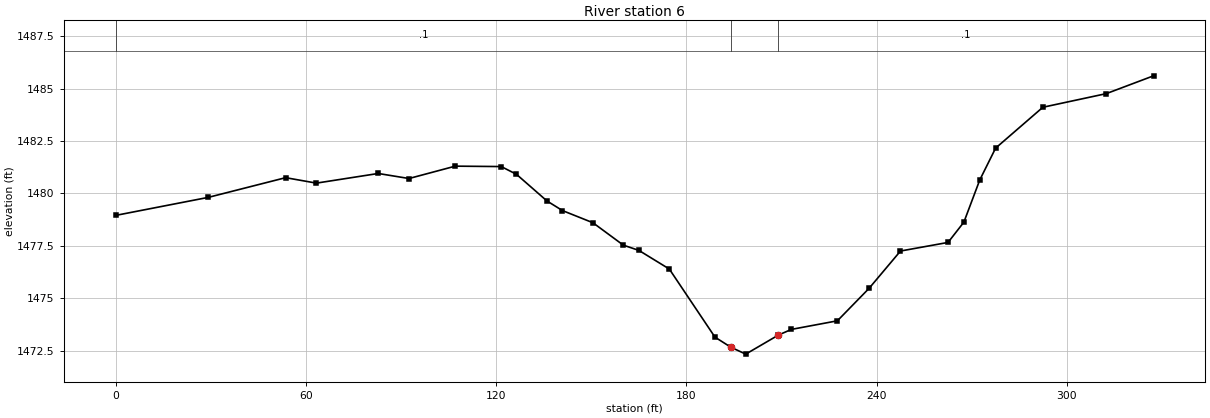
Type RM Length L Ch R = 1 ,6       ,14.9,6,0
XS GIS Cut Line= 5
     1788254.832      277759.381     1788248.285      277866.318
     1788256.287      277962.342      1788258.47      277986.348
     1788297.752      278078.008
#Sta/Elev= 30
       0 1478.95    29.2 1479.81    53.6 1480.75    63.3 1480.49    82.8 1480.95
    92.5 1480.71   107.1  1481.3   121.6 1481.28   126.4 1480.91     136 1479.64
   140.9 1479.18   150.5  1478.6   160.1 1477.53     165 1477.28   174.6 1476.39
     189 1473.14     194 1472.66   198.7 1472.33     209 1473.24   213.1 1473.51
   227.6 1473.92   237.6 1475.47   247.5 1477.25   262.5 1477.66   267.5 1478.63
   272.5 1480.64   277.5 1482.16   292.4 1484.11   312.4 1484.76   327.3 1485.61
#Mann= 3 , 0 , 0
       0      .1       0     194    .045       0     209      .1       0
Bank Sta=194,209
XS Rating Curve= 0 ,0
Exp/Cntr=0.3,0.1

Chan Stop Cuts=-1
Use User Specified Reach Order=0